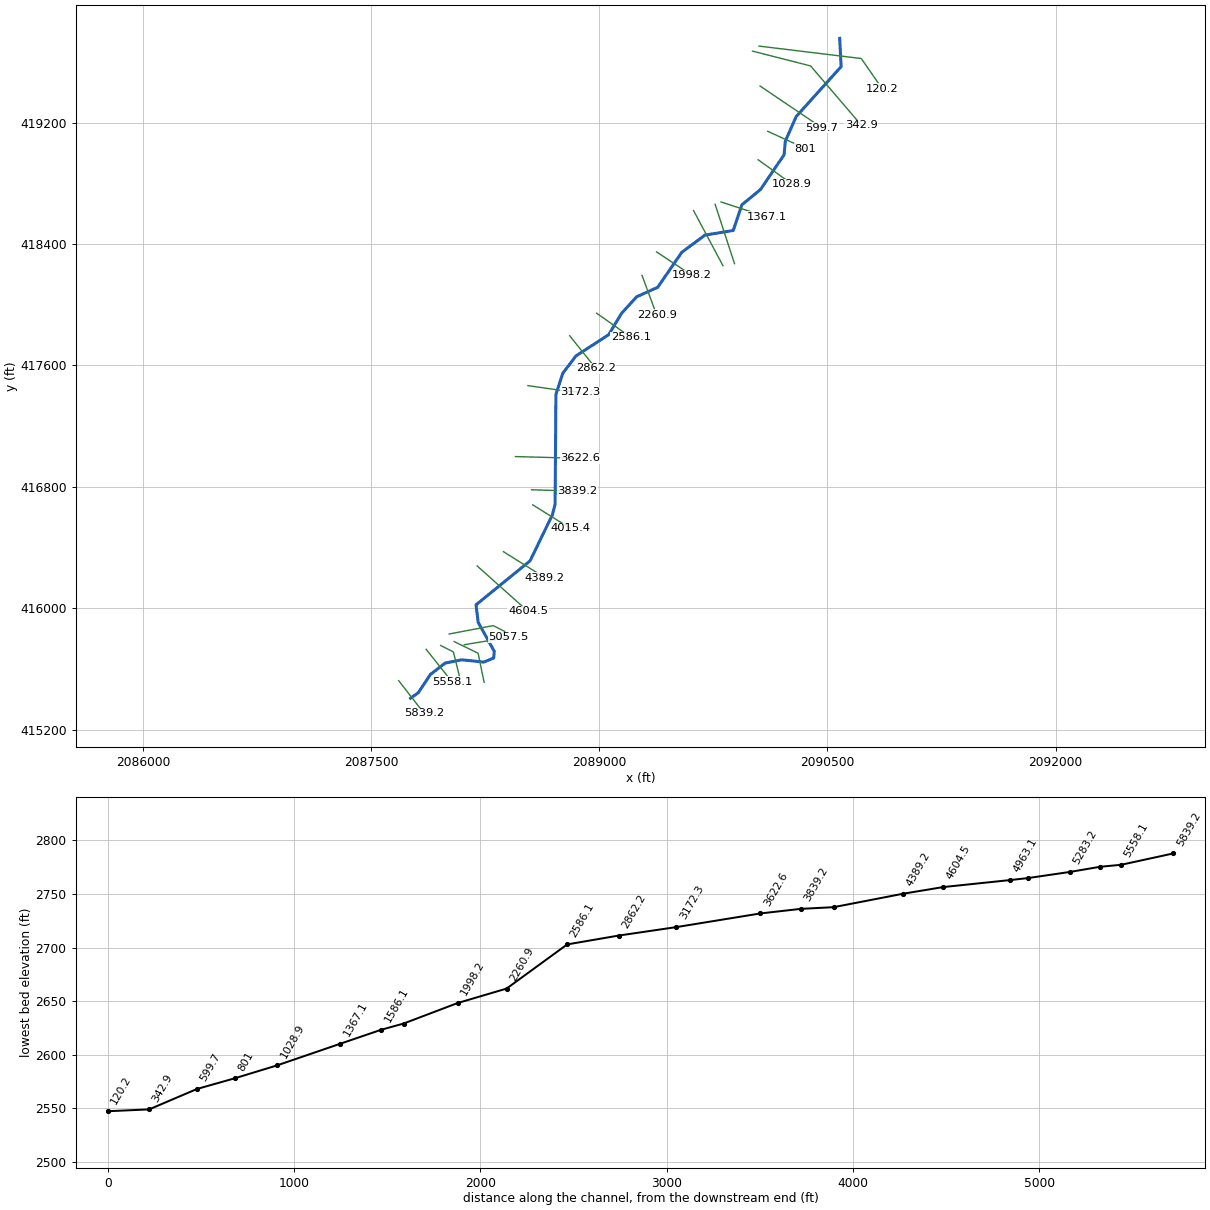
--- BeechRun.prj (project) ---

Proj Title=BeechRun
Current Plan=p01
Default Exp/Contr=0,0
English Units
Geom File=g01
Flow File=f01
Plan File=p01
BEGIN DESCRIPTION:
END DESCRIPTION:
DSS Export Rating Curves= 0
DSS Export Rating Curve Sorted= 0
DSS Export Volume Flow Curves= 0
DXF OffsetX= 0
DXF OffsetY= 0
DXF ScaleX= 0
DXF ScaleY= 0

--- BeechRun.p01 (plan) ---

Plan Title=Floodplain
Program Version=4.00
Geom File=g01
Flow File=f01
K Sum by GR=0
Std Step Tol=0.01
Critical Tol=0.01
Num of Std Step Trials=20
Max Error Tol=0.3
Flow Tol Ratio=0.001
Split Flow NTrial=30
Split Flow Tol=0.02
Split Flow Ratio=0.02
Log Output Level=0
Friction Slope Method=1
Unsteady Friction Slope Method=2
Unsteady Bridges Friction Slope Method=1
Global Log Level=0
CheckData=False
Run HTab=0
Run UNet=0
Run PostProcess=0
UNET Theta=0
UNET Theta Warmup=0
UNET ZTol=0
UNET ZSATol=0
UNET MxIter=0
UNET MaxInSteps=0
UNET DtIC=0
UNET DtMin=0
UNET MaxCRTS=0
UNET WFStab=0
UNET SFStab=0
UNET WFX=0
UNET SFX=0
UNET DSS MLevel=0
UNET DZMax Abort=0
UNET Convert EG Bridges=0
UNET Use Existing IB Tables=0
UNET Froude Limit=0
UNET Froude Power=0
Write IC File=0
Echo Input=False
Echo Output=False
Write Detailed=0

--- BeechRun.f01 (steady flow) ---

Flow Title=NFF Regression Equation
Program Version=4.00
Number of Profiles=1
Profile Names=P100yr
River Rch & RM=BeechRun,Main      ,5839.2
531.5361
River Rch & RM=BeechRun,Main      ,5283.2
590.3180
River Rch & RM=BeechRun,Main      ,4015.4
606.2731
River Rch & RM=BeechRun,Main      ,120.2
667.1486
Boundary for River Rch & Prof#=BeechRun,Main      ,1
Up Type=0
Dn Type=3
Dn Slope=0.042414

--- BeechRun.g01 (geometry) ---

Geom Title=USGS 10m DEM
Program Version=4.00

River Reach=BeechRun        ,Main
Reach XY= 30
     2087758.371      415407.109     2087809.907      415443.873
     2087888.408      415563.027     2087985.834      415638.725
     2088095.876      415660.453     2088240.432      415645.307
     2088305.446      415672.368     2088308.951      415716.525
     2088203.114      415907.872     2088189.096       416022.82
      2088544.51      416312.467     2088690.943      416615.084
     2088709.167      416685.175     2088714.406      417409.185
     2088759.816      417549.055     2088846.736      417663.423
     2089061.905       417803.18     2089145.923      417943.397
     2089245.443      418052.792     2089383.708      418115.195
     2089542.094      418345.973     2089694.499      418459.023
     2089880.484      418489.612     2089937.351      418658.884
     2090059.744      418759.667     2090214.755        418988.4
     2090223.172      419078.362     2090294.464      419240.622
     2090590.018      419569.363     2090580.558      419755.904

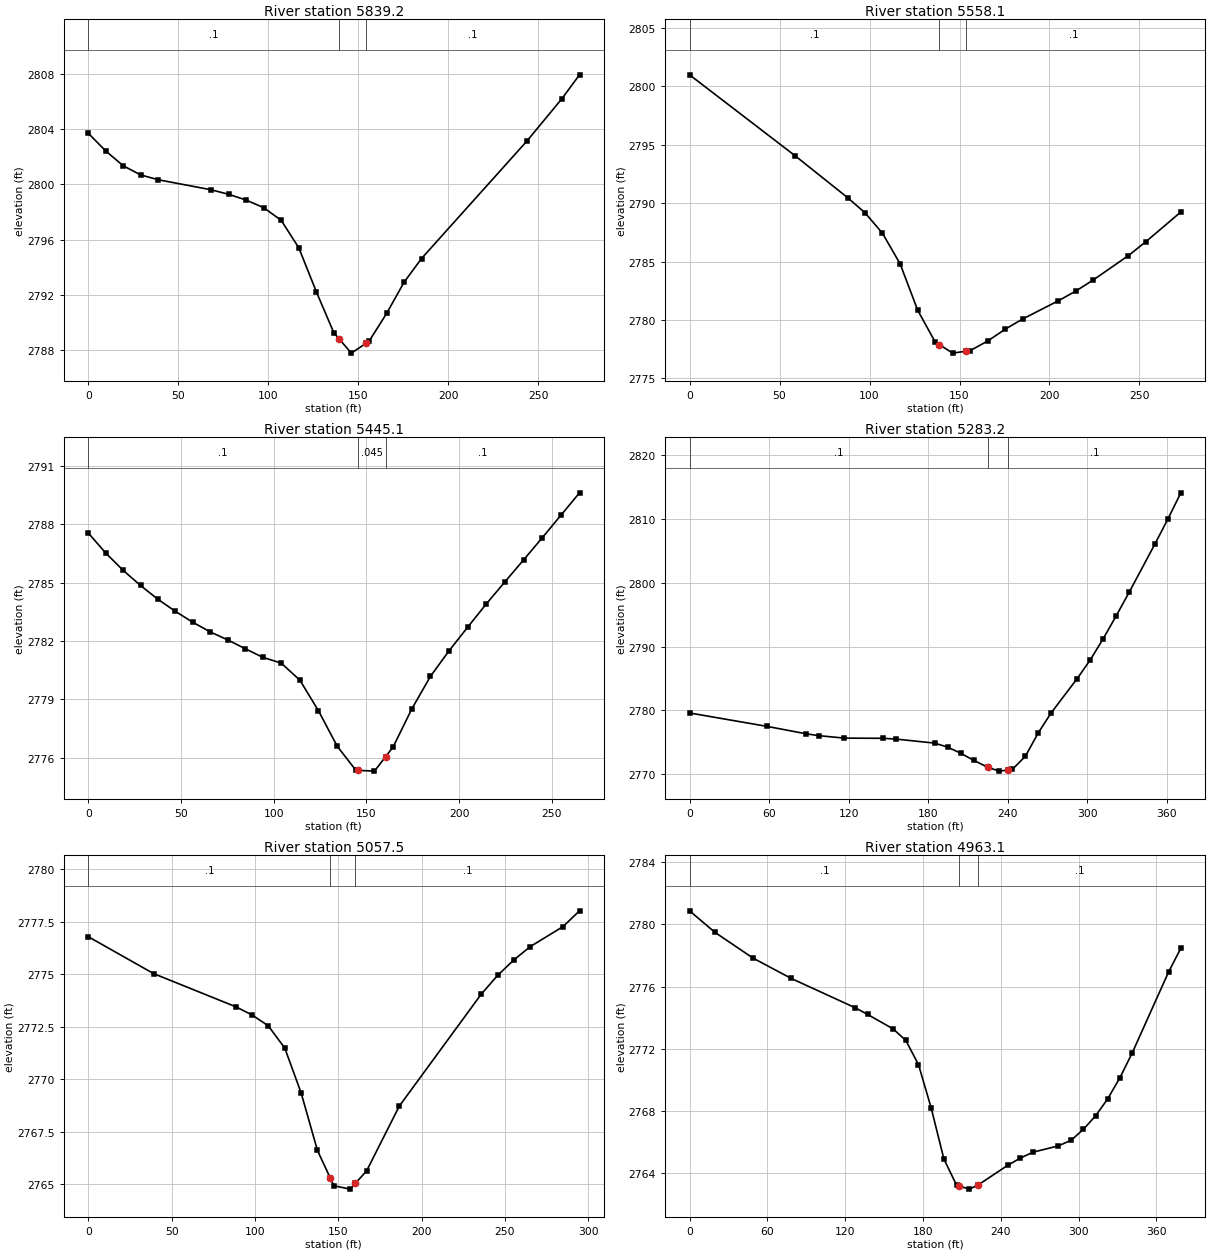
Type RM Length L Ch R = 1 ,5839.2  ,285,281,281.1
XS GIS Cut Line= 3
     2087680.532        415522.9     2087764.323      415415.145
     2087848.115      415307.389
#Sta/Elev= 23
       0 2803.71     9.8 2802.42    19.5 2801.35    29.2 2800.69      39 2800.34
    68.2 2799.62      78 2799.29    87.8 2798.87    97.5 2798.32   107.2 2797.41
     117 2795.42   126.8 2792.22   136.5 2789.26   139.4 2788.82   146.2 2787.79
   154.4  2788.5     156 2788.64   165.8 2790.66   175.5 2792.92   185.2 2794.64
   243.8 2803.15   263.2 2806.21     273 2807.94
#Mann= 3 , 0 , 0
       0      .1       0   139.4    .045       0   154.4      .1       0
Bank Sta=139.4,154.4
XS Rating Curve= 0 ,0
Exp/Cntr=0.3,0.1

Type RM Length L Ch R = 1 ,5558.1  ,123.1,113,103
XS GIS Cut Line= 2
     2087861.151      415729.642     2088030.868      415515.808
#Sta/Elev= 21
       0 2800.99    58.5 2794.08    87.8 2790.48    97.5 2789.18   107.2 2787.43
     117 2784.81   126.8 2780.83   136.5 2778.12   138.8  2777.9   146.2 2777.17
   153.8 2777.34     156 2777.39   165.8 2778.22   175.5 2779.23   185.2  2780.1
   204.8 2781.64   214.5 2782.47   224.2 2783.42   243.8 2785.51   253.5  2786.7
     273 2789.25
#Mann= 3 , 0 , 0
       0      .1       0   138.8    .045       0   153.8      .1       0
Bank Sta=138.8,153.8
XS Rating Curve= 0 ,0
Exp/Cntr=0.3,0.1

Type RM Length L Ch R = 1 ,5445.1  ,162.7,161.9,161.1
XS GIS Cut Line= 3
     2087956.598      415754.891     2088040.404      415712.133
     2088081.452       415546.23
#Sta/Elev= 30
       0 2787.55     9.4 2786.52    18.8 2785.63    28.2 2784.85    37.6 2784.14
      47 2783.52    56.4 2782.96    65.9 2782.46    75.3 2782.05    84.7  2781.6
    94.1 2781.16   104.1 2780.86   114.2 2779.98   124.2 2778.41   134.3 2776.59
   144.4 2775.35   145.4 2775.35   154.4 2775.31   160.4 2776.05   164.5 2776.56
   174.5  2778.5   184.6 2780.18   194.6 2781.49   204.7 2782.71   214.7  2783.9
   224.8 2785.04   234.8 2786.16   244.9  2787.3   254.9 2788.45     265 2789.61
#Mann= 3 , 0 , 0
       0      .1       0   145.4    .045       0   160.4      .1       0
Bank Sta=145.4,160.4
XS Rating Curve= 0 ,0
Exp/Cntr=0.3,0.1

Type RM Length L Ch R = 1 ,5283.2  ,190.5,225.7,260.9
XS GIS Cut Line= 3
     2088045.535      415780.546     2088202.886      415703.581
     2088242.223      415512.024
#Sta/Elev= 26
       0 2779.61    58.4 2777.51    87.6 2776.36    97.3 2776.06   116.8 2775.67
     146 2775.64   155.7 2775.52   184.9 2774.89   194.7 2774.26   204.5 2773.31
   214.3  2772.2   225.3 2771.07   233.8  2770.5   240.3 2770.68   243.6 2770.78
   253.4 2772.83   263.2 2776.53   272.9 2779.64   292.5    2785   302.3 2787.91
     312  2791.2   321.8 2794.78   331.6 2798.48   351.2  2806.1   360.9 2809.98
   370.7 2814.09
#Mann= 3 , 0 , 0
       0      .1       0   225.3    .045       0   240.3      .1       0
Bank Sta=225.3,240.3
XS Rating Curve= 0 ,0
Exp/Cntr=0.3,0.1

Type RM Length L Ch R = 1 ,5057.5  ,94.1,94.5,94.9
XS GIS Cut Line= 2
     2088112.238      415760.022     2088402.995      415807.911
#Sta/Elev= 20
       0 2776.78    39.3 2775.02    88.4 2773.45    98.2 2773.06     108 2772.54
   117.9 2771.48   127.7 2769.35   137.5 2766.61   145.3 2765.28   147.3 2764.93
   157.2 2764.77   160.3 2765.05     167 2765.64   186.6 2768.72   235.7 2774.04
   245.6 2774.94   255.4 2775.68   265.2 2776.31   284.8 2777.26   294.7 2778.01
#Mann= 3 , 0 , 0
       0      .1       0   145.3    .045       0   160.3      .1       0
Bank Sta=145.3,160.3
XS Rating Curve= 0 ,0
Exp/Cntr=0.3,0.1

Type RM Length L Ch R = 1 ,4963.1  ,379.6,358.6,337.6
XS GIS Cut Line= 3
     2088012.831      415830.508     2088301.806      415885.709
     2088377.346      415847.648
#Sta/Elev= 27
       0 2780.88    19.6 2779.49      49 2777.83    78.4 2776.52   127.5 2774.64
   137.3  2774.2   156.9 2773.27   166.7 2772.53   176.5 2770.97   186.3 2768.17
   196.1 2764.88   205.9 2763.19   207.7 2763.14   215.8 2762.94   222.7 2763.22
   245.2 2764.47     255 2764.94   264.8 2765.32   284.4 2765.73   294.2 2766.09
   303.6 2766.79     313 2767.66   322.4 2768.76   331.8 2770.12   341.2  2771.7
   369.4 2776.95   378.8 2778.47
#Mann= 3 , 0 , 0
       0      .1       0   207.7    .045       0   222.7      .1       0
Bank Sta=207.7,222.7
XS Rating Curve= 0 ,0
Exp/Cntr=0.3,0.1

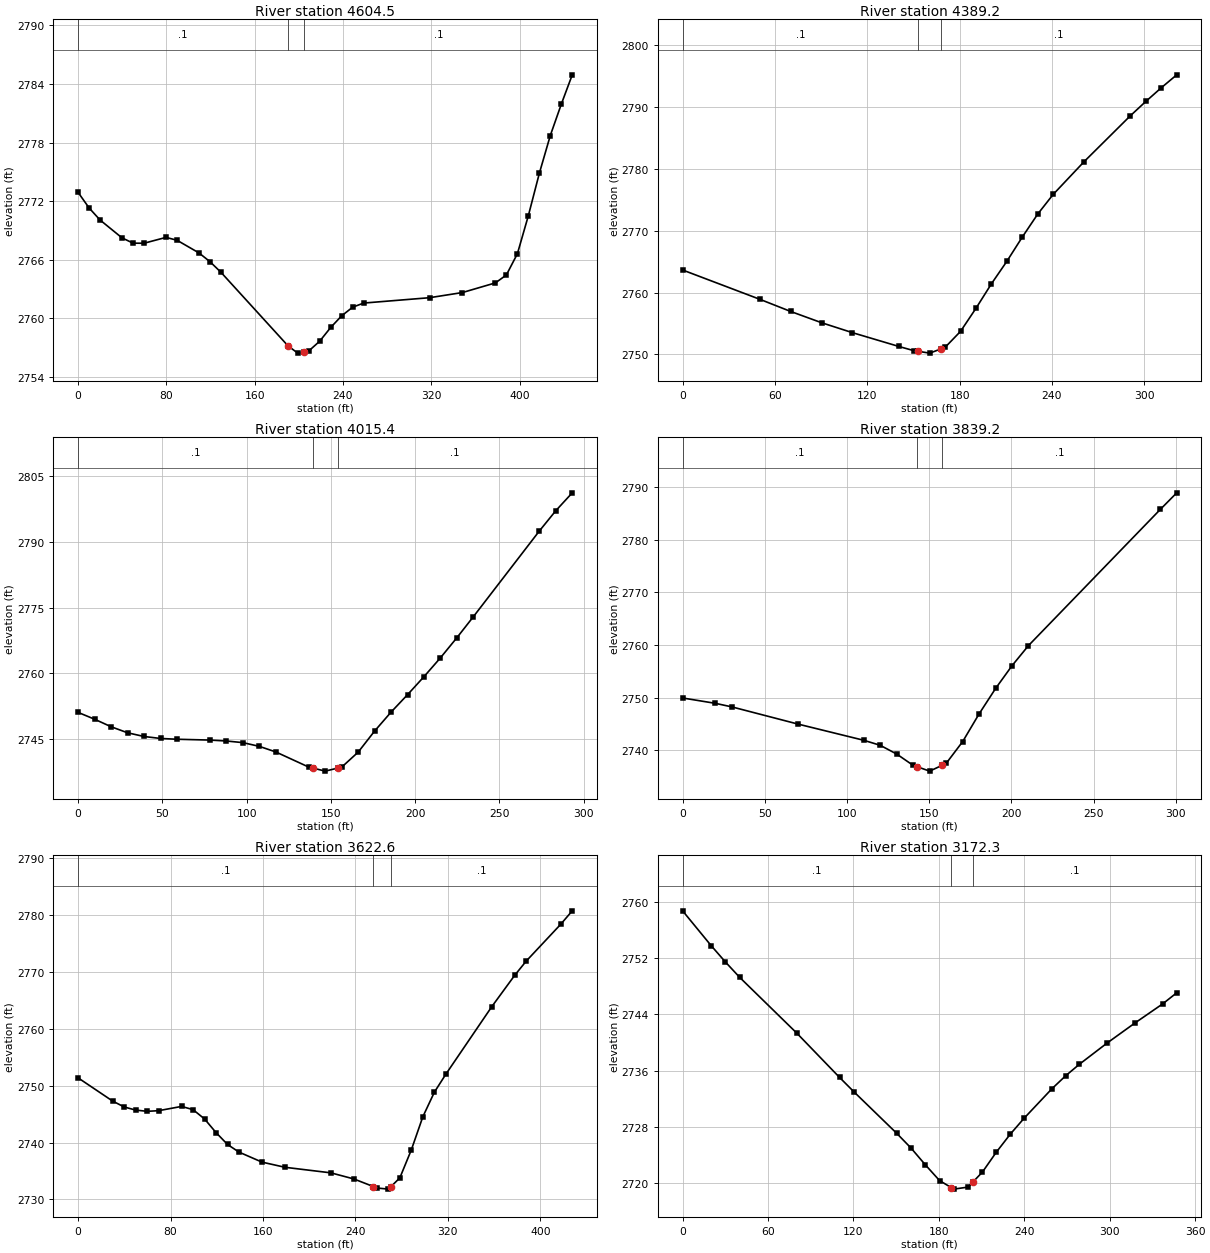
Type RM Length L Ch R = 1 ,4604.5  ,211.1,215.3,219.4
XS GIS Cut Line= 2
     2088196.775      416278.731      2088530.52      415980.117
#Sta/Elev= 30
       0 2772.89      10 2771.29    19.9 2770.06    39.8 2768.23    49.8 2767.69
    59.7 2767.68    79.6 2768.28    89.6 2767.99   109.5 2766.69   119.4  2765.8
   129.4 2764.71   190.1 2757.18     199 2756.42   205.1 2756.55     209 2756.64
   218.9 2757.64   228.9 2759.05   238.8 2760.24   248.8 2761.13   258.8 2761.55
   318.5  2762.1   348.3 2762.63   378.2 2763.62   388.1 2764.43   398.1 2766.61
     408  2770.5     418 2774.86   427.9 2778.72   437.9 2781.94   447.8 2784.94
#Mann= 3 , 0 , 0
       0      .1       0   190.1    .045       0   205.1      .1       0
Bank Sta=190.1,205.1
XS Rating Curve= 0 ,0
Exp/Cntr=0.3,0.1

Type RM Length L Ch R = 1 ,4389.2  ,373.7,373.8,373.9
XS GIS Cut Line= 2
     2088369.543      416373.019      2088641.32      416201.973
#Sta/Elev= 23
       0 2763.64    50.2 2758.91    70.2 2756.95    90.3 2755.13   110.4 2753.52
   140.5  2751.3   150.5  2750.6   153.1 2750.51   160.6 2750.22   168.1 2750.92
   170.6 2751.16   180.6 2753.73   190.7 2757.48   200.7 2761.42   210.7 2765.04
   220.8 2768.98   230.8 2772.68   240.8 2775.84   260.9 2781.13     291 2788.55
     301 2790.85   311.1 2793.07   321.1 2795.15
#Mann= 3 , 0 , 0
       0      .1       0   153.1    .045       0   168.1      .1       0
Bank Sta=153.1,168.1
XS Rating Curve= 0 ,0
Exp/Cntr=0.3,0.1

Type RM Length L Ch R = 1 ,4015.4  ,164.3,176.2,188.1
XS GIS Cut Line= 2
     2088562.132      416681.532     2088810.741      416526.102
#Sta/Elev= 28
       0 2751.06     9.8  2749.5    19.6 2747.78    29.3 2746.41    39.1 2745.56
    48.9 2745.11    58.6 2744.93    78.2 2744.74      88 2744.53    97.7 2744.16
   107.5 2743.31   117.3 2742.03   136.8 2738.58   139.1 2738.37   146.6 2737.65
   154.1 2738.35   156.4 2738.56   166.2    2742   175.9 2746.79   185.7 2751.13
   195.5 2755.12   205.2 2759.21     215 2763.53   224.8 2768.14   234.6 2772.95
   273.6 2792.45   283.4  2797.1   293.2  2801.2
#Mann= 3 , 0 , 0
       0      .1       0   139.1    .045       0   154.1      .1       0
Bank Sta=139.1,154.1
XS Rating Curve= 0 ,0
Exp/Cntr=0.3,0.1

Type RM Length L Ch R = 1 ,3839.2  ,216.5,216.6,216.8
XS GIS Cut Line= 2
     2088554.489      416781.057      2088854.97      416771.508
#Sta/Elev= 19
       0 2749.95      20 2748.93    30.1 2748.25    70.2    2745   110.2 2741.93
   120.2 2740.98   130.3 2739.31   140.3 2737.16   142.8  2736.9   150.3 2736.08
   157.8 2737.17   160.3 2737.53   170.4 2741.69   180.4 2746.95   190.4 2751.75
   200.4 2756.07   210.4 2759.88   290.6  2785.7   300.6 2788.85
#Mann= 3 , 0 , 0
       0      .1       0   142.8    .045       0   157.8      .1       0
Bank Sta=142.8,157.8
XS Rating Curve= 0 ,0
Exp/Cntr=0.3,0.1

Type RM Length L Ch R = 1 ,3622.6  ,453.8,450.3,450.3
XS GIS Cut Line= 2
     2088448.547      416999.738     2088875.975      416988.027
#Sta/Elev= 30
       0 2751.37    29.8  2747.3    39.8 2746.26    49.7 2745.71    59.7 2745.49
    69.6  2745.6    89.5 2746.35    99.4 2745.79   109.4 2744.15   119.3 2741.76
   129.3 2739.66   139.2 2738.32   159.1 2736.56     179 2735.65   218.8 2734.67
   238.6  2733.6   255.4 2732.27   258.5 2732.01   268.5 2731.81   270.4 2732.19
   278.4 2733.79   288.4 2738.74   298.3 2744.53   308.3 2748.86   318.2 2752.01
     358  2763.9   377.9 2769.43   387.8 2771.91   417.6 2778.37   427.6 2780.74
#Mann= 3 , 0 , 0
       0      .1       0   255.4    .045       0   270.4      .1       0
Bank Sta=255.4,270.4
XS Rating Curve= 0 ,0
Exp/Cntr=0.3,0.1

Type RM Length L Ch R = 1 ,3172.3  ,327.2,310,292.5
XS GIS Cut Line= 3
      2088530.52      417467.331     2088738.933      417437.264
     2088874.755      417423.672
#Sta/Elev= 26
       0 2758.78      20 2753.83    30.1 2751.48    40.1 2749.29    80.2 2741.34
   110.3 2735.01   120.3 2732.98   150.4 2727.05   160.4 2724.96   170.5 2722.56
   180.5 2720.31   188.8  2719.3   190.5 2719.09   200.5 2719.38   203.8 2720.08
   210.6 2721.52   220.3 2724.34   230.1 2726.91   239.8 2729.18   259.3 2733.38
   269.1 2735.26   278.8 2736.91   298.3 2739.94   317.8 2742.79   337.3 2745.52
   347.1 2747.09
#Mann= 3 , 0 , 0
       0      .1       0   188.8    .045       0   203.8      .1       0
Bank Sta=188.8,203.8
XS Rating Curve= 0 ,0
Exp/Cntr=0.3,0.1

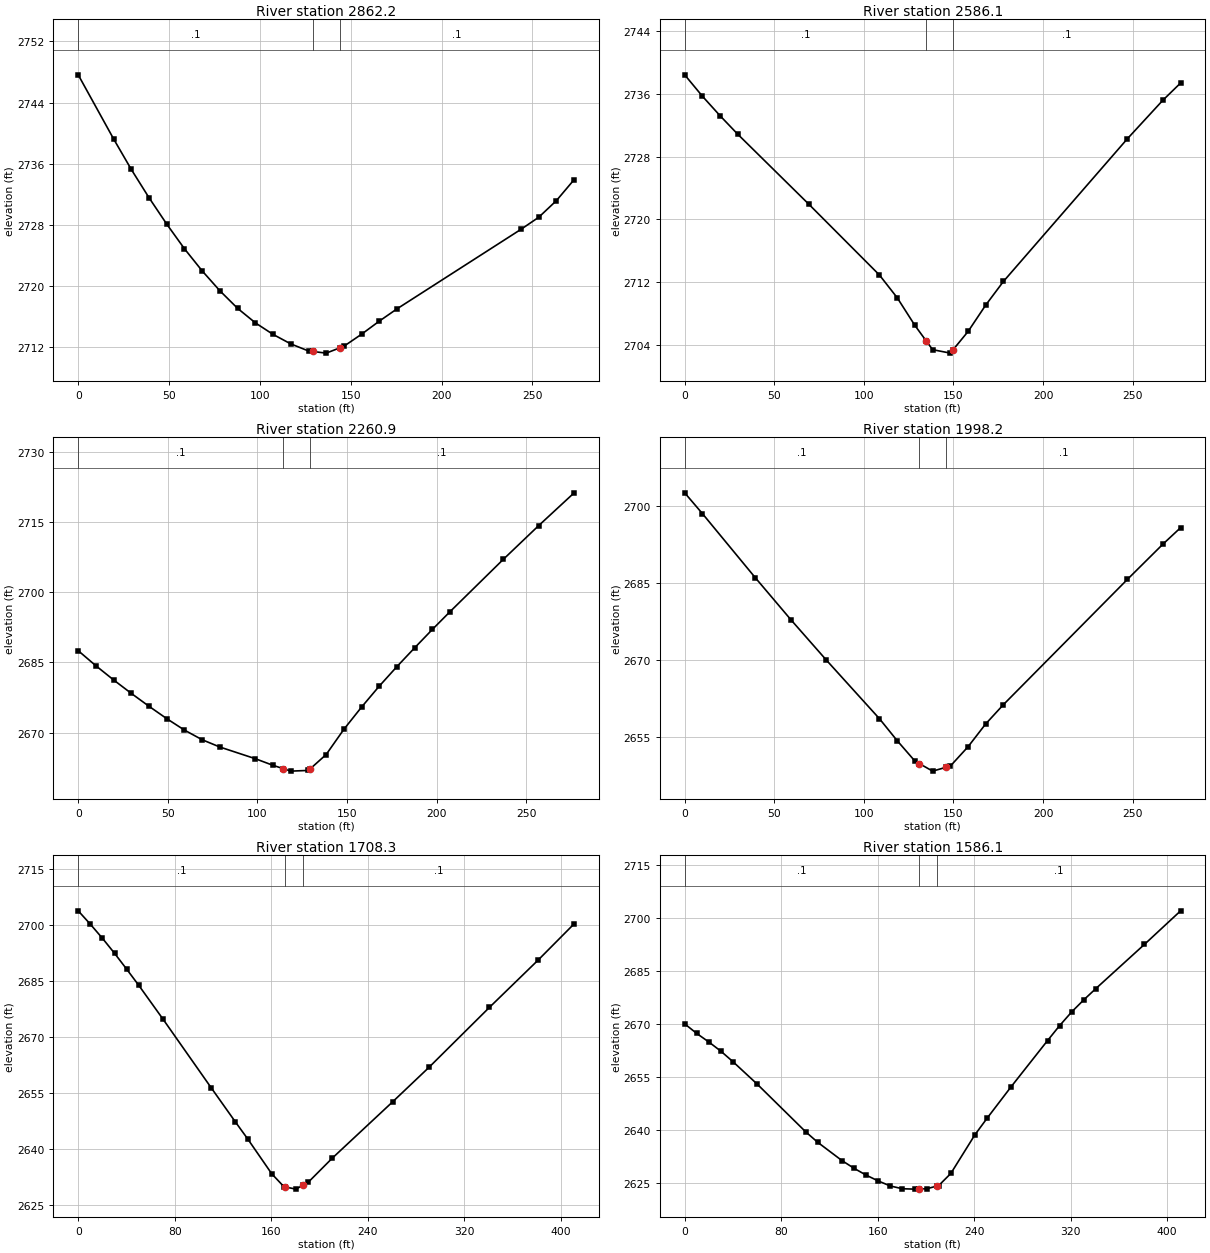
Type RM Length L Ch R = 1 ,2862.2  ,269.9,276.2,282.5
XS GIS Cut Line= 2
     2088804.943      417795.862     2088975.601      417582.778
#Sta/Elev= 24
       0 2747.63    19.5 2739.23    29.2 2735.25      39 2731.53    48.8 2728.06
    58.5 2724.85    68.2 2721.97      78 2719.35    87.8 2717.04    97.5 2715.16
   107.2 2713.65     117  2712.4   126.8 2711.47     129 2711.41   136.5 2711.19
     144 2711.88   146.2 2712.08     156 2713.67   165.8 2715.39   175.5 2716.99
   243.8 2727.41   253.5 2728.98   263.2 2731.15     273 2733.91
#Mann= 3 , 0 , 0
       0      .1       0     129    .045       0     144      .1       0
Bank Sta=129,144
XS Rating Curve= 0 ,0
Exp/Cntr=0.3,0.1

Type RM Length L Ch R = 1 ,2586.1  ,339.1,325.2,314.5
XS GIS Cut Line= 2
     2088982.419      417944.292     2089208.713      417784.937
#Sta/Elev= 18
       0 2738.43     9.9  2735.7    19.8  2733.2    29.6 2730.86    69.2 2721.95
   108.7  2712.9   118.6 2710.01   128.5 2706.47   134.8  2704.5   138.4 2703.38
   148.3 2702.94   149.8 2703.37   158.2 2705.71     168 2709.06   177.9 2712.08
   247.1 2730.28   266.9 2735.19   276.8 2737.39
#Mann= 3 , 0 , 0
       0      .1       0   134.8    .045       0   149.8      .1       0
Bank Sta=134.8,149.8
XS Rating Curve= 0 ,0
Exp/Cntr=0.3,0.1

Type RM Length L Ch R = 1 ,2260.9  ,248.3,262.6,278.9
XS GIS Cut Line= 2
     2089280.977       418193.03     2089376.808      417933.378
#Sta/Elev= 26
       0 2687.48     9.9 2684.25    19.8 2681.22    29.6 2678.37    39.5 2675.61
    49.4 2672.97    59.3 2670.52    69.2 2668.46    79.1  2666.9    98.8 2664.42
   108.7    2663   114.2 2662.32   118.6 2661.76   128.5 2661.91   129.2 2662.15
   138.4 2665.31   148.3  2670.7   158.2 2675.46     168  2679.9   177.9 2684.09
   187.8  2688.1   197.7 2692.03   207.6 2695.84   237.2 2706.96     257 2714.19
   276.8 2721.19
#Mann= 3 , 0 , 0
       0      .1       0   114.2    .045       0   129.2      .1       0
Bank Sta=114.2,129.2
XS Rating Curve= 0 ,0
Exp/Cntr=0.3,0.1

Type RM Length L Ch R = 1 ,1998.2  ,301.2,290,278.7
XS GIS Cut Line= 2
      2089376.32      418348.471     2089606.947      418195.456
#Sta/Elev= 18
       0 2702.53     9.9 2698.48    39.5 2685.95    59.3 2677.79    79.1 2669.92
   108.7 2658.51   118.6 2654.23   128.5 2650.25   130.9 2649.77   138.4 2648.29
   145.9 2649.04   148.3 2649.28   158.2 2653.06     168 2657.49   177.9 2661.25
   247.1 2685.66   266.9 2692.52   276.8 2695.74
#Mann= 3 , 0 , 0
       0      .1       0   130.9    .045       0   145.9      .1       0
Bank Sta=130.9,145.9
XS Rating Curve= 0 ,0
Exp/Cntr=0.3,0.1

Type RM Length L Ch R = 1 ,1708.3  ,126,122.2,118.4
XS GIS Cut Line= 2
     2089619.582      418620.799     2089812.802      418257.779
#Sta/Elev= 22
       0 2703.79      10 2700.22    20.1 2696.42    30.1 2692.41    40.1 2688.18
    50.2 2683.81    70.2 2674.79   110.3 2656.32   130.4 2647.15   140.4 2642.68
   160.5 2633.26   170.5 2629.83   171.6 2629.75   180.5 2629.16   186.6 2630.25
   190.6 2630.96   210.6 2637.45   260.8  2652.6   290.9 2661.84     341 2677.91
   381.2 2690.54   411.2 2700.31
#Mann= 3 , 0 , 0
       0      .1       0   171.6    .045       0   186.6      .1       0
Bank Sta=171.6,186.6
XS Rating Curve= 0 ,0
Exp/Cntr=0.3,0.1

Type RM Length L Ch R = 1 ,1586.1  ,197.7,219,240.4
XS GIS Cut Line= 2
     2089761.447      418662.145     2089888.833      418271.133
#Sta/Elev= 30
       0 2670.03      10 2667.31    20.1 2664.88    30.1 2662.27    40.1  2659.3
    60.2 2652.95   100.3 2639.49   110.3 2636.51   130.4 2631.34   140.4 2629.16
   150.4 2627.23   160.5 2625.57   170.5 2624.15   180.5 2623.37   190.6 2623.26
   194.5  2623.3   200.6 2623.36   209.5 2624.16   210.6 2624.26   220.7 2627.71
   240.7 2638.67   250.8 2643.35   270.8 2652.29   300.9 2665.31   310.9 2669.54
     321 2673.45     331 2676.85     341 2680.03   381.2 2692.51   411.2 2702.01
#Mann= 3 , 0 , 0
       0      .1       0   194.5    .045       0   209.5      .1       0
Bank Sta=194.5,209.5
XS Rating Curve= 0 ,0
Exp/Cntr=0.3,0.1

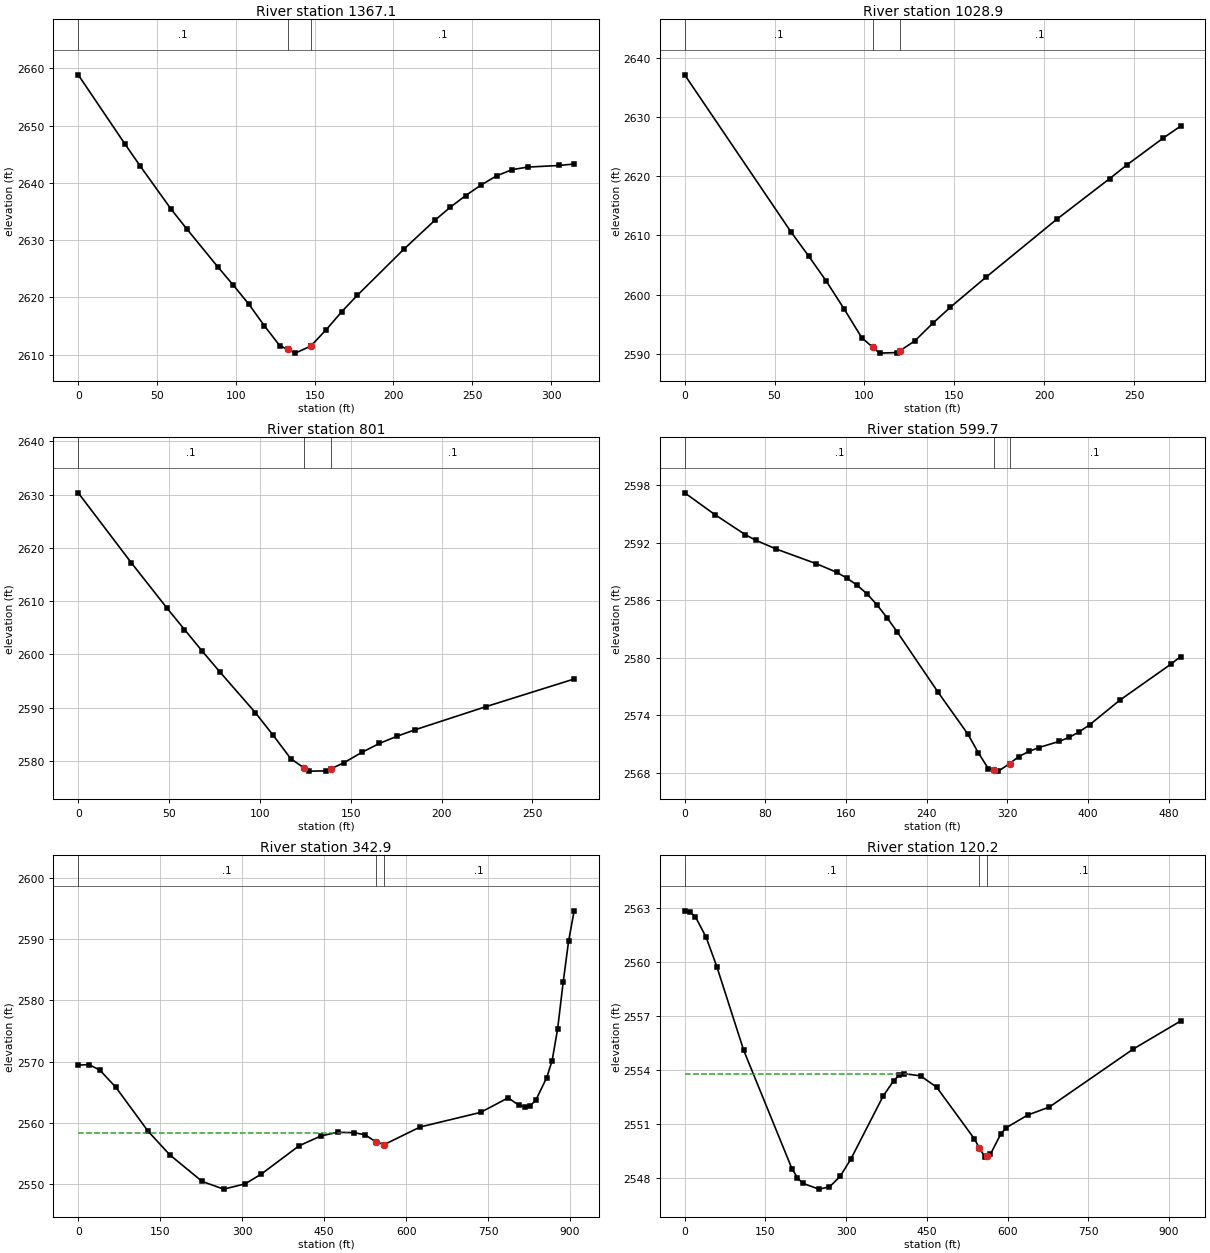
Type RM Length L Ch R = 1 ,1367.1  ,345.5,338.1,345.7
XS GIS Cut Line= 2
     2089800.512       418677.49     2090099.706      418579.813
#Sta/Elev= 27
       0 2658.88    29.5 2646.86    39.3 2642.96      59 2635.39    68.8 2631.99
    88.5 2625.35    98.4 2622.14   108.2 2618.84     118 2615.08   127.9 2611.56
   132.9  2610.9   137.7 2610.26   147.5 2611.48   147.9 2611.59   157.4 2614.36
   167.2 2617.49     177 2620.33   206.5 2628.38   226.2 2633.44     236 2635.73
   245.9 2637.79   255.7 2639.64   265.6 2641.25   275.4 2642.32   285.2 2642.76
   304.9 2643.04   314.7  2643.3
#Mann= 3 , 0 , 0
       0      .1       0   132.9    .045       0   147.9      .1       0
Bank Sta=132.9,147.9
XS Rating Curve= 0 ,0
Exp/Cntr=0.3,0.1

Type RM Length L Ch R = 1 ,1028.9  ,223.3,227.9,232.5
XS GIS Cut Line= 2
     2090044.132      418955.726     2090268.231      418794.821
#Sta/Elev= 19
       0 2637.13    59.1 2610.62      69 2606.51    78.8 2602.28    88.7 2597.59
    98.5 2592.74   104.6 2591.13   108.4 2590.13   118.2 2590.23   119.6  2590.5
   128.1 2592.21   137.9 2595.14   147.8 2597.88   167.5 2602.92   206.9 2612.71
   236.5 2619.62   246.3 2621.98     266  2626.4   275.9 2628.47
#Mann= 3 , 0 , 0
       0      .1       0   104.6    .045       0   119.6      .1       0
Bank Sta=104.6,119.6
XS Rating Curve= 0 ,0
Exp/Cntr=0.3,0.1

Type RM Length L Ch R = 1 ,801     ,205.1,201.3,197.5
XS GIS Cut Line= 2
     2090107.418      419143.169      2090355.71      419029.679
#Sta/Elev= 20
       0 2630.32    29.2  2617.2    48.8  2608.7    58.5 2604.65    68.2 2600.62
      78 2596.68    97.5 2589.05   107.2 2584.84     117 2580.41   124.1  2578.7
   126.8 2578.06   136.5  2578.1   139.1  2578.5   146.2 2579.62     156 2581.56
   165.8 2583.26   175.5 2584.61   185.2  2585.8   224.2 2590.14     273 2595.36
#Mann= 3 , 0 , 0
       0      .1       0   124.1    .045       0   139.1      .1       0
Bank Sta=124.1,139.1
XS Rating Curve= 0 ,0
Exp/Cntr=0.3,0.1

Type RM Length L Ch R = 1 ,599.7   ,262.9,256.8,250.7
XS GIS Cut Line= 2
     2090056.806       419441.75     2090464.215      419166.064
#Sta/Elev= 30
       0 2597.21    30.1 2594.93    60.2 2592.84    70.3 2592.28    90.4 2591.36
   130.5 2589.82   150.6 2588.93   160.6 2588.33   170.7  2587.6   180.7 2586.69
   190.7 2585.53   200.8 2584.17   210.8  2582.7     251 2576.46   281.1 2572.01
   291.1 2570.12   301.2 2568.44   307.2 2568.29   311.2 2568.18   322.2 2568.96
   331.3 2569.69   341.3 2570.23   351.4 2570.64   371.4 2571.28   381.5 2571.71
   391.5 2572.29   401.6 2573.01   431.7 2575.59   481.9 2579.31   491.9 2580.13
#Mann= 3 , 0 , 0
       0      .1       0   307.2    .045       0   322.2      .1       0
Bank Sta=307.2,322.2
XS Rating Curve= 0 ,0
Exp/Cntr=0.3,0.1

Type RM Length L Ch R = 1 ,342.9   ,205.7,222.7,239.7
XS GIS Cut Line= 3
     2090007.498       419671.68     2090389.406      419574.004
     2090722.567      419183.664
#Sta/Elev= 30
       0 2569.41    19.7 2569.49    39.4 2568.61      69 2565.77   128.1 2558.57
   167.5 2554.74   226.7 2550.39   266.1 2549.13   305.5 2549.99   335.1  2551.6
   404.3 2556.23   444.5 2557.84   474.7 2558.43   504.9 2558.36     525 2558.01
   544.9 2556.83   559.9 2556.42   625.6 2559.29   736.3 2561.68   786.6 2564.06
   806.8 2562.82   816.8 2562.62   826.9 2562.78     837 2563.63   857.1 2567.35
   867.1 2570.14   877.2 2575.37   887.3 2582.96   897.3 2589.72   907.4 2594.64
#Mann= 3 , 0 , 0
       0      .1       0   544.9    .045       0   559.9      .1       0
#XS Ineff= 2 , 0
          494.24 2558.39
Permanent Ineff=
       F       F
Bank Sta=544.9,559.9
XS Rating Curve= 0 ,0
Exp/Cntr=0.3,0.1

Type RM Length L Ch R = 1 ,120.2   ,112.2,120.2,128.2
XS GIS Cut Line= 3
     2090050.066      419704.789     2090722.452      419622.917
     2090861.433      419422.278
#Sta/Elev= 30
       0 2562.84      10 2562.78    19.9 2562.51    39.8 2561.38    59.8 2559.74
   109.6 2555.11   199.2 2548.55   209.2 2548.05   219.1 2547.74     249 2547.41
     269 2547.53   288.9 2548.12   308.8 2549.08   368.6 2552.56   388.5 2553.43
   398.4 2553.72   408.4 2553.81   438.3 2553.69   468.2 2553.06   537.9 2550.21
   547.1 2549.71   557.8  2549.2   562.1 2549.26   567.8 2549.33   587.7 2550.49
   597.7 2550.82   637.5 2551.52   677.4 2551.96   833.6 2555.18   921.4 2556.73
#Mann= 3 , 0 , 0
       0      .1       0   547.1    .045       0   562.1      .1       0
#XS Ineff= 2 , 0
           416.3 2553.79
Permanent Ineff=
       F       F
Bank Sta=547.1,562.1
XS Rating Curve= 0 ,0
Exp/Cntr=0.3,0.1

Chan Stop Cuts=-1
Use User Specified Reach Order=0